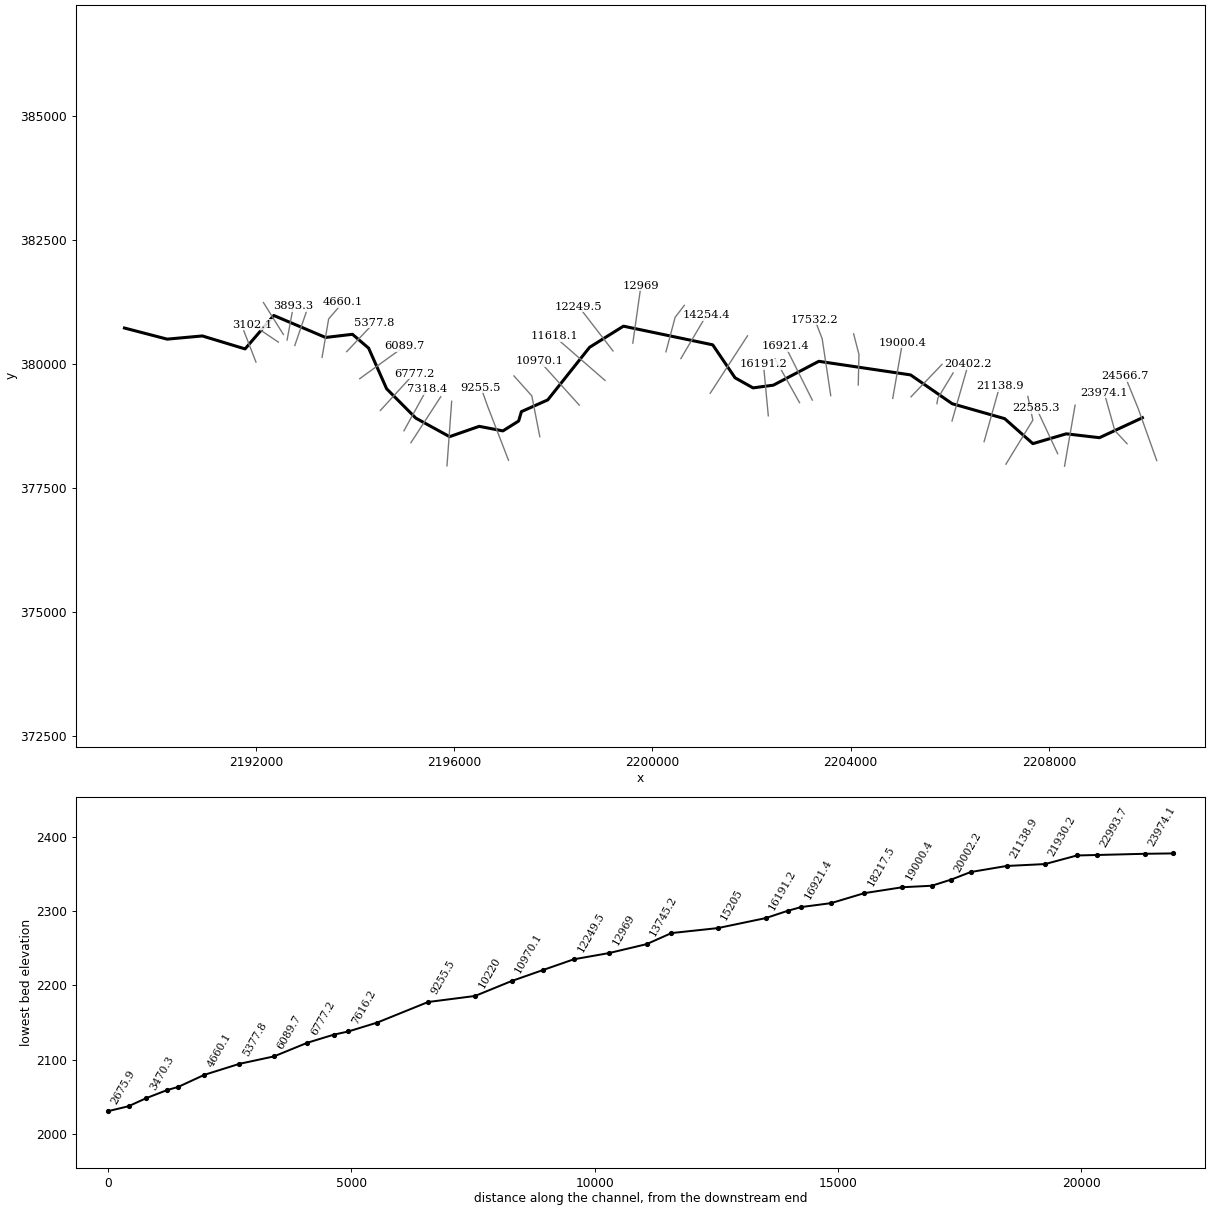
--- SpiceRun.prj (project) ---

Proj Title=SpiceRun
Current Plan=p01
Geom File=g01
Flow File=f01
Plan File=p01
DSS Export Rating Curves=0
DSS Export Rating Curve Sorted=0
DSS Export Volume Flow Curves=0
DXF OffsetX=0
DXF OffsetY=0
DXF ScaleX=0
DXF ScaleY=0

--- SpiceRun.p01 (plan) ---

Plan Title=Floodplain
Program Version=4.00
Geom File=g01
Flow File=f01
K Sum by GR=0
Std Step Tol=0.01
Critical Tol=0.01
Num of Std Step Trials=20
Max Error Tol=0.3
Flow Tol Ratio=0.001
Split Flow NTrial=30
Split Flow Tol=0.02
Split Flow Ratio=0.02
Log Output Level=0
Friction Slope Method=1
Unsteady Friction Slope Method=2
Unsteady Bridges Friction Slope Method=1
Global Log Level=0
CheckData=False
Run HTab=0
Run UNet=0
Run PostProcess=0
UNET Theta=0
UNET Theta Warmup=0
UNET ZTol=0
UNET ZSATol=0
UNET MxIter=0
UNET MaxInSteps=0
UNET DtIC=0
UNET DtMin=0
UNET MaxCRTS=0
UNET WFStab=0
UNET SFStab=0
UNET WFX=0
UNET SFX=0
UNET DSS MLevel=0
UNET DZMax Abort=0
UNET Convert EG Bridges=0
UNET Use Existing IB Tables=0
UNET Froude Limit=0
UNET Froude Power=0
Write IC File=0
Echo Input=False
Echo Output=False
Write Detailed=0

--- SpiceRun.f01 (steady flow) ---

Flow Title=NFF Regression Equation
Program Version=4.00
Number of Profiles=1
Profile Names=P100yr
River Rch & RM=SpiceRun,Main      ,24566.7
722.8619
River Rch & RM=SpiceRun,Main      ,23974.1
724.7635
River Rch & RM=SpiceRun,Main      ,22993.7
803.5632
River Rch & RM=SpiceRun,Main      ,21930.2
891.3210
River Rch & RM=SpiceRun,Main      ,19602.5
912.9184
River Rch & RM=SpiceRun,Main      ,19000.4
1083.181
River Rch & RM=SpiceRun,Main      ,16191.2
1185.167
River Rch & RM=SpiceRun,Main      ,11618.1
1316.210
River Rch & RM=SpiceRun,Main      ,10220
1440.862
River Rch & RM=SpiceRun,Main      ,6089.7
1496.628
River Rch & RM=SpiceRun,Main      ,228.7
1659.400
Boundary for River Rch & Prof#=SpiceRun,Main      ,1
Up Type=0
Dn Type=3
Dn Slope=0.024089

--- SpiceRun.g01 (geometry) ---

Geom Title=USGS 10m DEM
Program Version=4.00

River Reach=SpiceRun     ,Main
Reach XY= 30
     2209886.527      378919.014     2209019.876      378516.460
     2208349.737      378594.585     2207676.126      378396.668
     2207107.001      378900.951     2206048.837      379201.814
     2205207.863      379783.769     2203356.681      380058.127
     2202440.284      379576.728     2202029.490      379521.763
     2201666.429      379724.990     2201215.938      380390.481
     2199414.022      380767.073     2198730.831      380340.940
     2197886.907      379279.485     2197354.945      379042.502
     2197299.390      378853.266     2196981.681      378653.613
     2196502.515      378745.627     2195905.292      378537.293
     2195223.941      378911.269     2194634.459      379504.307
     2194271.612      380323.752     2193945.223      380603.265
     2193403.556      380539.029     2192357.944      380982.733
     2191778.556      380308.127     2190915.586      380569.888
     2190206.222      380505.403     2189344.415      380729.665

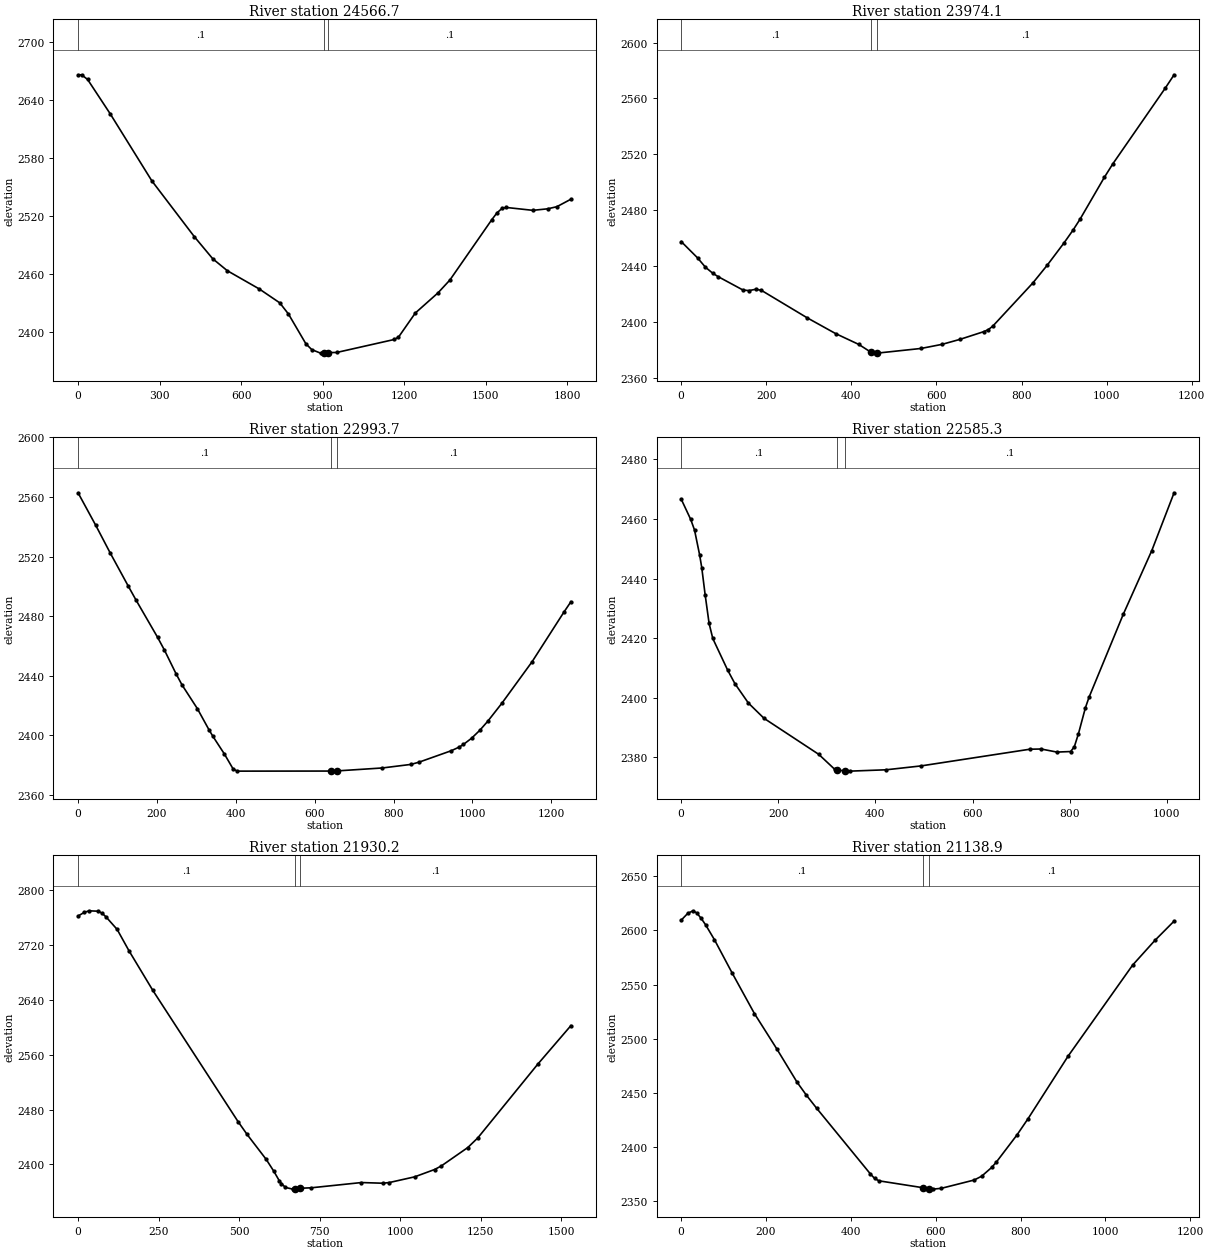
Type RM Length L Ch R = 1 ,24566.7,594.1,592.6,590.8
XS GIS Cut Line= 3
     2210176.131      378054.293     2209803.988      379098.573
     2209538.171      379751.723
#Sta/Elev= 30
       0 2665.93    13.2 2665.92    35.0 2661.17   118.2 2625.67   271.6 2556.26
   428.1 2498.49   495.6 2475.74   549.2 2463.39   666.8 2444.52   742.2 2430.16
   774.3 2418.58   838.6 2387.71   860.1 2381.79   892.2 2378.16   906.1 2378.33
   921.1 2378.76   951.3 2378.81  1163.6 2392.27  1179.1 2394.65  1241.1 2419.64
  1324.6 2440.48  1368.2 2453.72  1522.9 2516.30  1541.3 2523.07  1559.7 2527.76
  1575.4 2528.80  1673.5 2525.81  1728.0 2527.38  1761.9 2529.56  1813.8 2537.33
#Mann= 3 , 0 , 0
       0     0.1       0   906.1   0.045       0   921.1     0.1       0
Bank Sta=   906.1,   921.1
Exp/Cntr=0.3,0.1

Type RM Length L Ch R = 1 ,23974.1,990.6,980.4,970.1
XS GIS Cut Line= 3
     2209577.492      378394.502     2209330.067      378660.600
     2209115.322      379426.215
#Sta/Elev= 30
       0 2457.56    38.5 2445.86    57.1 2439.14    74.2 2434.86    86.7 2432.45
   145.4 2422.81   159.2 2422.43   175.7 2423.39   188.6 2422.59   295.7 2403.01
   362.8 2391.67   417.7 2383.84   446.4 2378.21   459.7 2377.64   461.4 2377.66
   563.9 2380.99   613.4 2383.94   655.8 2387.54   711.4 2393.04   721.8 2394.46
   732.3 2396.93   826.7 2427.93   860.1 2440.50   900.0 2456.64   921.1 2465.77
   937.1 2473.34   994.5 2503.46  1014.7 2513.26  1137.6 2567.33  1158.5 2576.95
#Mann= 3 , 0 , 0
       0     0.1       0   446.4   0.045       0   461.4     0.1       0
Bank Sta=   446.4,   461.4
Exp/Cntr=0.3,0.1

Type RM Length L Ch R = 1 ,22993.7,394.4,408.5,422.5
XS GIS Cut Line= 2
     2208315.803      377941.759     2208528.603      379173.542
#Sta/Elev= 30
       0 2562.72    44.9 2540.90    81.4 2522.43   126.8 2500.39   147.3 2490.63
   201.6 2465.81   219.1 2457.19   248.8 2441.17   263.6 2433.87   302.5 2417.96
   331.8 2403.86   342.0 2399.34   371.2 2387.46   393.3 2377.43   403.5 2376.01
   641.5 2376.06   656.5 2376.15   772.0 2378.14   844.2 2380.52   864.6 2382.01
   946.6 2389.71   967.1 2392.22   977.4 2393.93   997.9 2398.06  1018.4 2403.28
  1038.8 2409.40  1074.6 2421.47  1151.6 2449.46  1231.8 2482.55  1250.0 2489.68
#Mann= 3 , 0 , 0
       0     0.1       0   641.5   0.045       0   656.5     0.1       0
Bank Sta=   641.5,   656.5
Exp/Cntr=0.3,0.1

Type RM Length L Ch R = 1 ,22585.3,679.3,655.1,630.8
XS GIS Cut Line= 2
     2208176.977      378193.762     2207747.486      379113.433
#Sta/Elev= 30
       0 2466.64    19.6 2459.84    27.5 2456.26    38.1 2447.84    42.4 2443.62
    49.3 2434.62    57.5 2424.94    65.1 2419.88    95.5 2409.34   110.7 2404.72
   138.4 2398.23   170.7 2393.09   283.3 2381.02   315.8 2376.06   321.5 2375.80
   336.5 2375.45   347.8 2375.39   422.2 2375.84   494.0 2377.14   718.0 2382.74
   741.2 2382.81   773.7 2381.78   802.0 2381.96   809.6 2383.55   818.2 2387.98
   832.4 2396.63   840.0 2400.21   910.4 2428.00   969.2 2449.39  1015.0 2468.74
#Mann= 3 , 0 , 0
       0     0.1       0   321.5   0.045       0   336.5     0.1       0
Bank Sta=   321.5,   336.5
Exp/Cntr=0.3,0.1

Type RM Length L Ch R = 1 ,21930.2,784,791.3,798.5
XS GIS Cut Line= 3
     2207132.685      377982.324     2207676.130      378871.283
     2207575.097      379349.511
#Sta/Elev= 30
       0 2762.52    19.3 2767.82    34.0 2770.08    63.3 2769.53    75.3 2766.26
    87.1 2761.09   121.3 2742.98   158.1 2711.79   232.3 2653.83   496.7 2462.48
   525.0 2443.58   584.2 2407.25   607.9 2389.92   624.7 2376.17   631.5 2371.94
   644.0 2366.23   667.0 2363.78   674.4 2364.12   689.4 2365.05   724.4 2365.73
   880.1 2373.39   946.8 2372.39   966.8 2373.42  1045.3 2381.71  1107.2 2392.42
  1127.8 2397.53  1210.4 2424.52  1241.4 2438.57  1427.1 2545.89  1530.7 2602.56
#Mann= 3 , 0 , 0
       0     0.1       0   674.4   0.045       0   689.4     0.1       0
Bank Sta=   674.4,   689.4
Exp/Cntr=0.3,0.1

Type RM Length L Ch R = 1 ,21138.9,736.8,736.7,736.6
XS GIS Cut Line= 2
     2206692.085      378435.638     2207006.267      379554.126
#Sta/Elev= 30
       0 2609.42    15.4 2615.66    27.6 2618.06    36.4 2616.22    46.9 2611.23
    57.4 2605.27    78.3 2591.49   120.3 2560.57   172.7 2523.21   225.2 2490.75
   273.2 2459.88   295.0 2447.99   319.6 2435.72   445.4 2375.52   455.9 2371.05
   466.4 2368.85   570.1 2362.49   585.1 2361.55   593.8 2361.20   613.2 2361.94
   690.8 2369.62   708.4 2373.17   731.8 2381.18   743.1 2386.26   791.6 2411.24
   817.8 2426.31   911.9 2483.87  1064.2 2568.00  1116.6 2590.75  1161.8 2608.54
#Mann= 3 , 0 , 0
       0     0.1       0   570.1   0.045       0   585.1     0.1       0
Bank Sta=   570.1,   585.1
Exp/Cntr=0.3,0.1

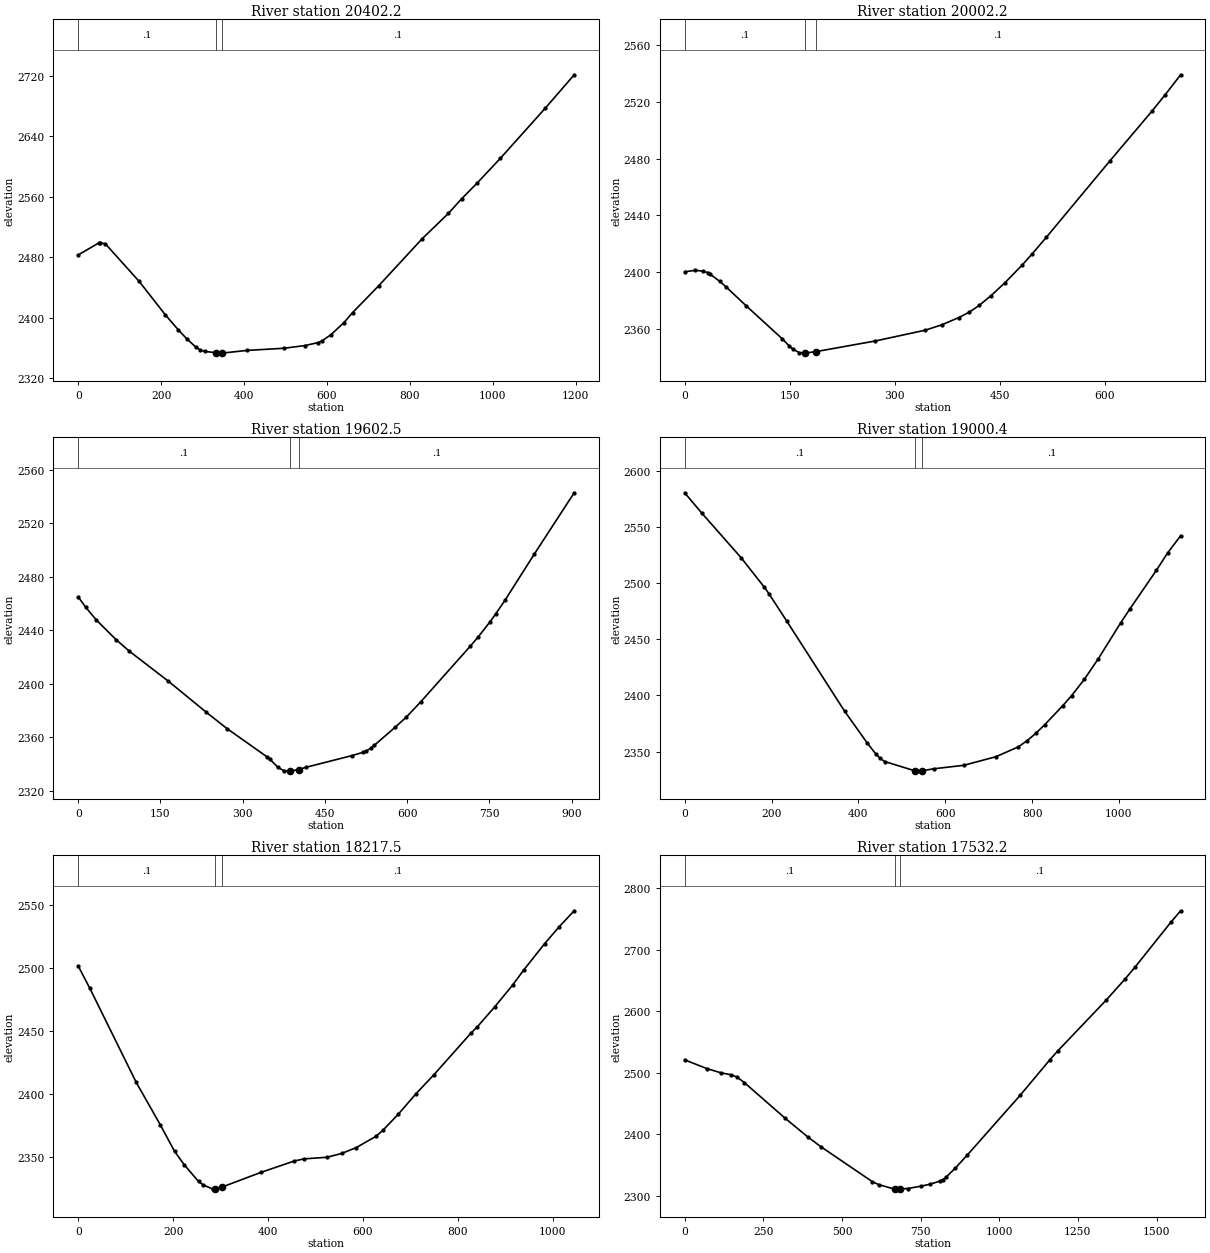
Type RM Length L Ch R = 1 ,20402.2,406,400,394
XS GIS Cut Line= 2
     2206044.576      378854.343     2206374.320      380003.961
#Sta/Elev= 30
       0 2482.88    49.2 2498.54    52.6 2499.12    65.6 2497.50   147.0 2447.85
   210.1 2403.68   241.6 2383.65   262.6 2371.49   283.7 2361.00   294.0 2357.38
   304.7 2355.44   331.8 2353.52   346.7 2353.03   346.8 2353.04   407.6 2356.63
   496.3 2359.48   546.8 2363.04   577.8 2366.87   587.0 2368.92   609.3 2377.28
   640.8 2393.42   661.8 2406.65   724.9 2442.24   829.9 2504.50   892.9 2537.85
   924.4 2556.94   962.6 2578.20  1017.8 2610.44  1126.8 2677.15  1196.0 2720.98
#Mann= 3 , 0 , 0
       0     0.1       0   331.8   0.045       0   346.8     0.1       0
Bank Sta=   331.8,   346.8
Exp/Cntr=0.3,0.1

Type RM Length L Ch R = 1 ,20002.2,404.7,399.7,394.7
XS GIS Cut Line= 3
     2205740.081      379202.133     2205758.754      379314.174
     2206066.868      379823.028
#Sta/Elev= 30
       0 2400.27    15.3 2401.28    26.2 2400.65    32.8 2399.71    36.4 2398.51
    50.4 2393.42    59.2 2389.56    87.6 2376.35   139.6 2352.87   148.8 2348.17
   154.5 2345.68   163.6 2343.26   170.9 2342.86   172.3 2342.91   187.3 2343.90
   272.5 2351.46   343.4 2359.01   367.0 2362.78   391.5 2367.95   406.2 2371.66
   420.9 2376.60   437.8 2383.50   457.7 2392.62   481.8 2404.85   496.8 2413.12
   516.5 2424.53   607.4 2478.48   667.5 2513.59   685.7 2524.74   708.4 2539.18
#Mann= 3 , 0 , 0
       0     0.1       0   172.3   0.045       0   187.3     0.1       0
Bank Sta=   172.3,   187.3
Exp/Cntr=0.3,0.1

Type RM Length L Ch R = 1 ,19602.5,588.8,602.1,615.6
XS GIS Cut Line= 2
     2205217.222      379342.184     2205842.785      379995.758
#Sta/Elev= 30
       0 2464.76    14.0 2456.91    33.2 2447.46    68.9 2432.92    93.5 2424.12
   163.4 2402.12   233.2 2378.70   271.5 2366.34   345.1 2345.01   349.9 2343.40
   364.5 2337.30   376.0 2334.64   386.9 2334.53   401.9 2335.67   415.0 2337.35
   498.9 2346.09   518.9 2348.51   525.2 2349.57   533.2 2351.52   540.3 2353.89
   578.5 2367.46   598.2 2374.80   624.7 2386.28   715.0 2427.84   729.6 2434.85
   750.5 2445.80   761.7 2452.14   778.4 2462.23   831.8 2496.68   904.7 2542.63
#Mann= 3 , 0 , 0
       0     0.1       0   386.9   0.045       0   401.9     0.1       0
Bank Sta=   386.9,   401.9
Exp/Cntr=0.3,0.1

Type RM Length L Ch R = 1 ,19000.4,779.4,782.9,786.2
XS GIS Cut Line= 2
     2204848.420      379309.505     2205044.492      380434.586
#Sta/Elev= 30
       0 2580.46    40.2 2562.07   129.6 2522.81   183.7 2496.23   194.0 2490.59
   235.0 2466.22   368.2 2385.95   419.5 2358.03   439.9 2347.93   450.2 2343.89
   460.5 2341.10   531.5 2332.63   536.0 2332.53   546.5 2332.80   573.2 2334.60
   642.7 2337.72   716.7 2345.37   768.0 2354.07   788.5 2359.66   809.0 2366.38
   829.5 2374.04   870.5 2390.80   891.0 2399.78   920.1 2414.21   952.5 2432.66
  1003.7 2464.46  1024.8 2476.80  1086.0 2511.32  1112.1 2526.92  1142.0 2542.22
#Mann= 3 , 0 , 0
       0     0.1       0   531.5   0.045       0   546.5     0.1       0
Bank Sta=   531.5,   546.5
Exp/Cntr=0.3,0.1

Type RM Length L Ch R = 1 ,18217.5,680.8,685.3,689
XS GIS Cut Line= 3
     2204152.831      379580.272     2204166.836      380196.498
     2204059.463      380611.984
#Sta/Elev= 30
       0 2501.46    24.5 2483.79   122.3 2409.20   172.8 2375.68   203.1 2354.52
   223.3 2343.96   253.6 2330.60   263.7 2327.86   283.9 2324.54   288.7 2324.70
   303.7 2326.26   384.9 2337.77   455.6 2346.86   475.8 2348.52   524.4 2349.81
   555.4 2352.83   586.4 2357.52   627.7 2366.40   642.1 2371.13   675.2 2384.12
   711.1 2399.79   749.8 2415.23   828.3 2448.41   841.0 2453.08   878.0 2469.05
   915.6 2486.29   939.8 2498.57   983.0 2519.07  1013.6 2532.47  1045.5 2545.23
#Mann= 3 , 0 , 0
       0     0.1       0   288.7   0.045       0   303.7     0.1       0
Bank Sta=   288.7,   303.7
Exp/Cntr=0.3,0.1

Type RM Length L Ch R = 1 ,17532.2,604.1,610.8,618.1
XS GIS Cut Line= 3
     2203597.293      379365.526     2203424.563      380513.948
     2203275.174      380901.424
#Sta/Elev= 30
       0 2520.97    70.9 2506.72   116.2 2499.81   146.8 2496.85   165.5 2493.36
   189.5 2484.19   319.4 2426.12   391.9 2395.60   434.8 2379.30   596.1 2323.31
   616.5 2318.43   667.6 2311.04   668.3 2311.05   683.3 2311.35   708.4 2311.97
   752.0 2315.90   779.9 2319.02   810.6 2323.90   820.8 2326.40   831.0 2330.51
   860.9 2345.56   898.6 2366.46  1066.9 2463.63  1161.3 2521.33  1186.7 2535.86
  1340.0 2617.99  1400.1 2652.32  1432.2 2671.91  1545.2 2744.27  1576.6 2763.00
#Mann= 3 , 0 , 0
       0     0.1       0   668.3   0.045       0   683.3     0.1       0
Bank Sta=   668.3,   683.3
Exp/Cntr=0.3,0.1

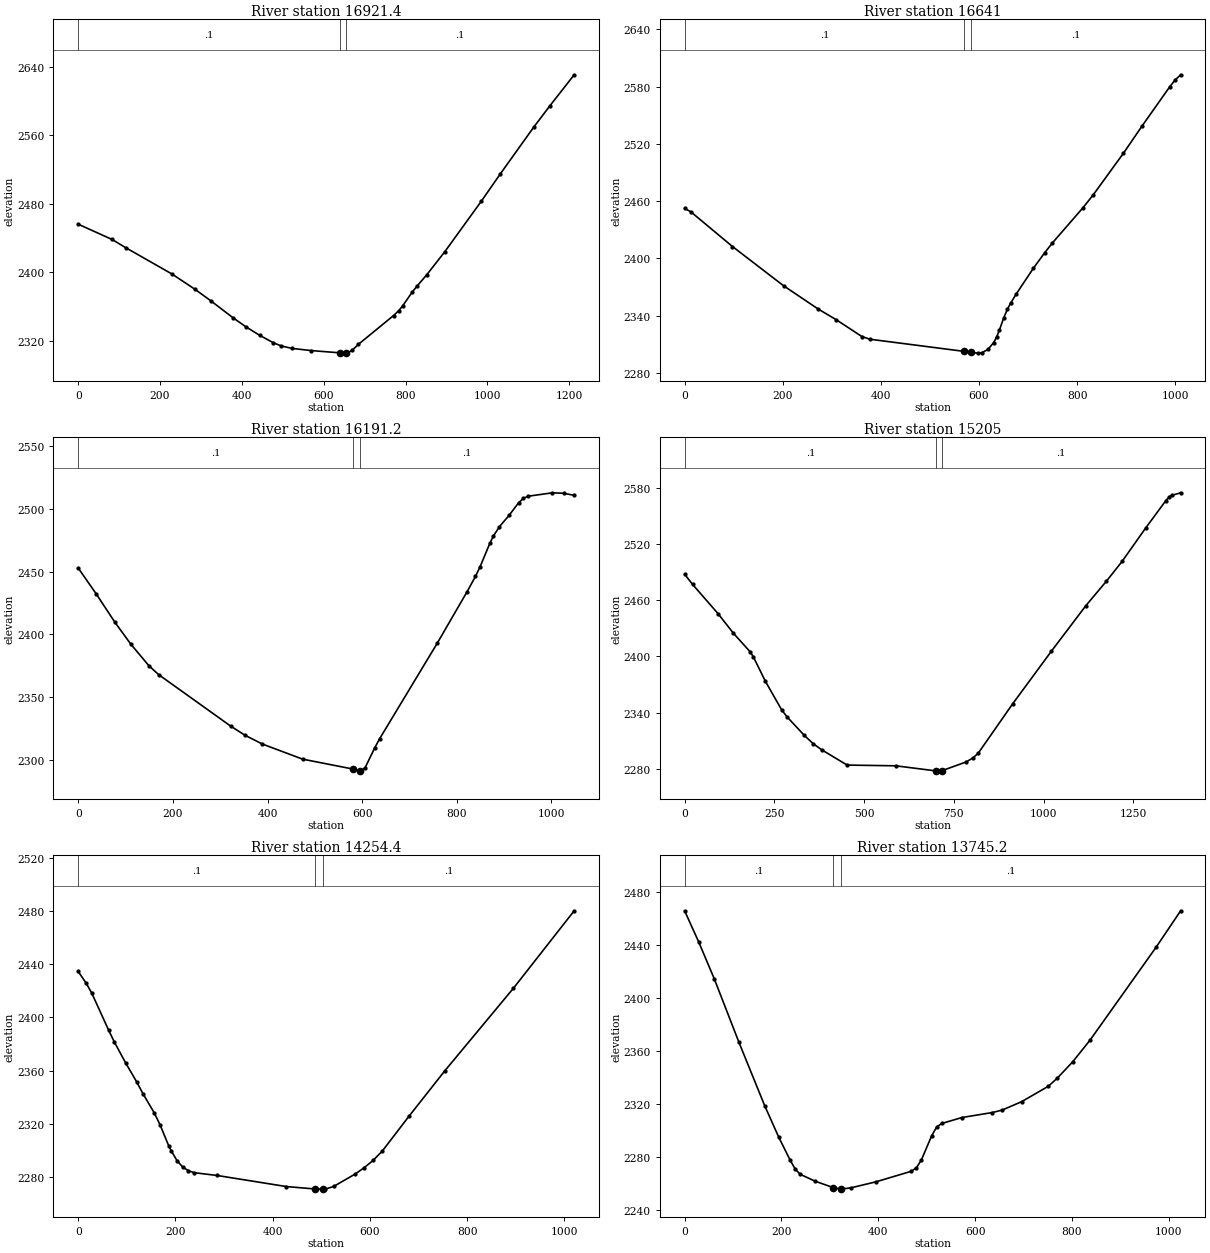
Type RM Length L Ch R = 1 ,16921.4,279.3,280.3,281.4
XS GIS Cut Line= 2
     2203224.980      379275.850     2202682.290      380359.892
#Sta/Elev= 30
       0 2456.36    82.8 2438.51   115.8 2429.02   228.8 2398.28   285.7 2380.26
   323.6 2367.03   377.6 2347.35   409.4 2336.68   443.3 2326.63   477.2 2317.85
   496.6 2314.13   522.4 2311.31   569.0 2308.79   639.6 2306.12   654.6 2305.78
   657.9 2305.93   669.2 2308.95   684.8 2316.01   770.8 2349.68   783.6 2355.40
   793.4 2361.26   816.0 2376.75   827.3 2383.62   851.3 2396.91   896.4 2424.46
   985.4 2483.26  1031.7 2515.10  1113.7 2569.89  1153.1 2594.76  1212.2 2630.80
#Mann= 3 , 0 , 0
       0     0.1       0   639.6   0.045       0   654.6     0.1       0
Bank Sta=   639.6,   654.6
Exp/Cntr=0.3,0.1

Type RM Length L Ch R = 1 ,16641,459.3,449.8,440.5
XS GIS Cut Line= 2
     2202967.645      379223.724     2202473.963      380106.048
#Sta/Elev= 30
       0 2452.29    12.4 2448.80    97.4 2412.39   201.6 2371.26   272.1 2346.90
   309.2 2335.59   361.2 2318.07   377.5 2315.24   569.6 2302.51   584.6 2301.37
   598.6 2300.67   606.0 2301.11   618.1 2304.50   629.7 2311.54   635.7 2317.26
   641.3 2324.46   650.5 2337.72   657.9 2346.68   664.4 2352.93   676.0 2362.72
   710.7 2389.50   733.8 2405.78   749.7 2416.18   811.8 2452.93   832.5 2466.27
   894.5 2510.16   932.4 2538.65   988.4 2579.45   999.2 2586.55  1011.0 2592.27
#Mann= 3 , 0 , 0
       0     0.1       0   569.6   0.045       0   584.6     0.1       0
Bank Sta=   569.6,   584.6
Exp/Cntr=0.3,0.1

Type RM Length L Ch R = 1 ,16191.2,999.2,986.1,972.9
XS GIS Cut Line= 2
     2202337.413      378957.626     2202239.377      380001.010
#Sta/Elev= 30
       0 2452.80    38.3 2432.04    77.6 2409.51   111.2 2392.08   149.8 2374.70
   170.1 2367.78   322.3 2326.74   352.7 2319.41   389.4 2312.43   474.4 2300.41
   581.3 2292.49   596.1 2290.88   596.3 2290.93   606.2 2293.54   626.5 2309.38
   636.7 2316.56   758.4 2392.66   821.6 2433.83   839.5 2446.15   849.4 2453.96
   869.9 2472.54   877.2 2478.21   890.2 2485.79   910.5 2494.78   930.8 2504.90
   940.9 2508.39   951.4 2510.07  1001.8 2512.74  1025.5 2512.39  1048.0 2510.76
#Mann= 3 , 0 , 0
       0     0.1       0   581.3   0.045       0   596.3     0.1       0
Bank Sta=   581.3,   596.3
Exp/Cntr=0.3,0.1

Type RM Length L Ch R = 1 ,15205,952.1,950.6,948.8
XS GIS Cut Line= 2
     2201164.482      379412.793     2201917.259      380571.720
#Sta/Elev= 30
       0 2487.87    22.0 2477.02    92.7 2445.88   135.7 2424.86   182.6 2404.90
   191.3 2399.60   225.1 2373.27   270.2 2342.93   284.8 2335.59   333.5 2315.54
   358.1 2306.73   381.7 2300.21   452.7 2283.83   588.3 2283.05   701.7 2277.52
   710.3 2277.36   716.7 2277.79   784.5 2287.18   803.3 2291.51   817.6 2296.28
   914.2 2349.46  1022.0 2405.65  1118.1 2454.35  1175.3 2480.49  1219.1 2501.72
  1284.7 2537.36  1340.6 2566.47  1350.5 2570.67  1357.0 2572.26  1382.0 2574.94
#Mann= 3 , 0 , 0
       0     0.1       0   701.7   0.045       0   716.7     0.1       0
Bank Sta=   701.7,   716.7
Exp/Cntr=0.3,0.1

Type RM Length L Ch R = 1 ,14254.4,501.3,509.3,516.9
XS GIS Cut Line= 2
     2200572.764      380113.051     2201090.955      380991.874
#Sta/Elev= 30
       0 2434.59    15.8 2426.08    27.5 2418.58    62.7 2390.27    74.4 2381.42
    97.8 2365.57   120.0 2351.63   133.0 2342.67   156.5 2328.05   168.2 2319.25
   186.3 2303.15   191.6 2299.35   203.4 2292.01   215.1 2287.25   226.8 2284.54
   238.5 2283.04   285.4 2280.96   428.3 2272.59   487.7 2270.76   502.7 2270.69
   508.2 2270.66   525.5 2272.69   569.8 2282.04   587.3 2286.55   606.6 2292.27
   625.4 2299.27   680.4 2325.55   753.8 2359.63   895.0 2421.84  1020.2 2480.27
#Mann= 3 , 0 , 0
       0     0.1       0   487.7   0.045       0   502.7     0.1       0
Bank Sta=   487.7,   502.7
Exp/Cntr=0.3,0.1

Type RM Length L Ch R = 1 ,13745.2,774.7,776.2,778
XS GIS Cut Line= 3
     2200271.653      380249.601     2200457.222      380946.357
     2200642.737      381186.955
#Sta/Elev= 30
       0 2465.70    29.0 2442.28    60.9 2414.67   111.9 2366.74   165.4 2318.62
   194.4 2294.90   217.6 2277.82   228.1 2271.02   238.5 2266.96   269.9 2261.67
     307 2256.89     322 2255.74   343.1 2256.68   395.3 2261.26   468.4 2269.23
   478.9 2271.88   489.3 2277.94   510.2 2295.89   520.7 2302.68   531.1 2305.27
   572.9 2309.79   635.6 2313.54   656.4 2315.46   696.0 2321.71   751.2 2333.32
   769.8 2339.47   801.6 2351.77   837.6 2368.20   974.2 2438.38  1024.7 2465.77
#Mann= 3 , 0 , 0
       0     0.1       0     307   0.045       0     322     0.1       0
Bank Sta=     307,     322
Exp/Cntr=0.3,0.1

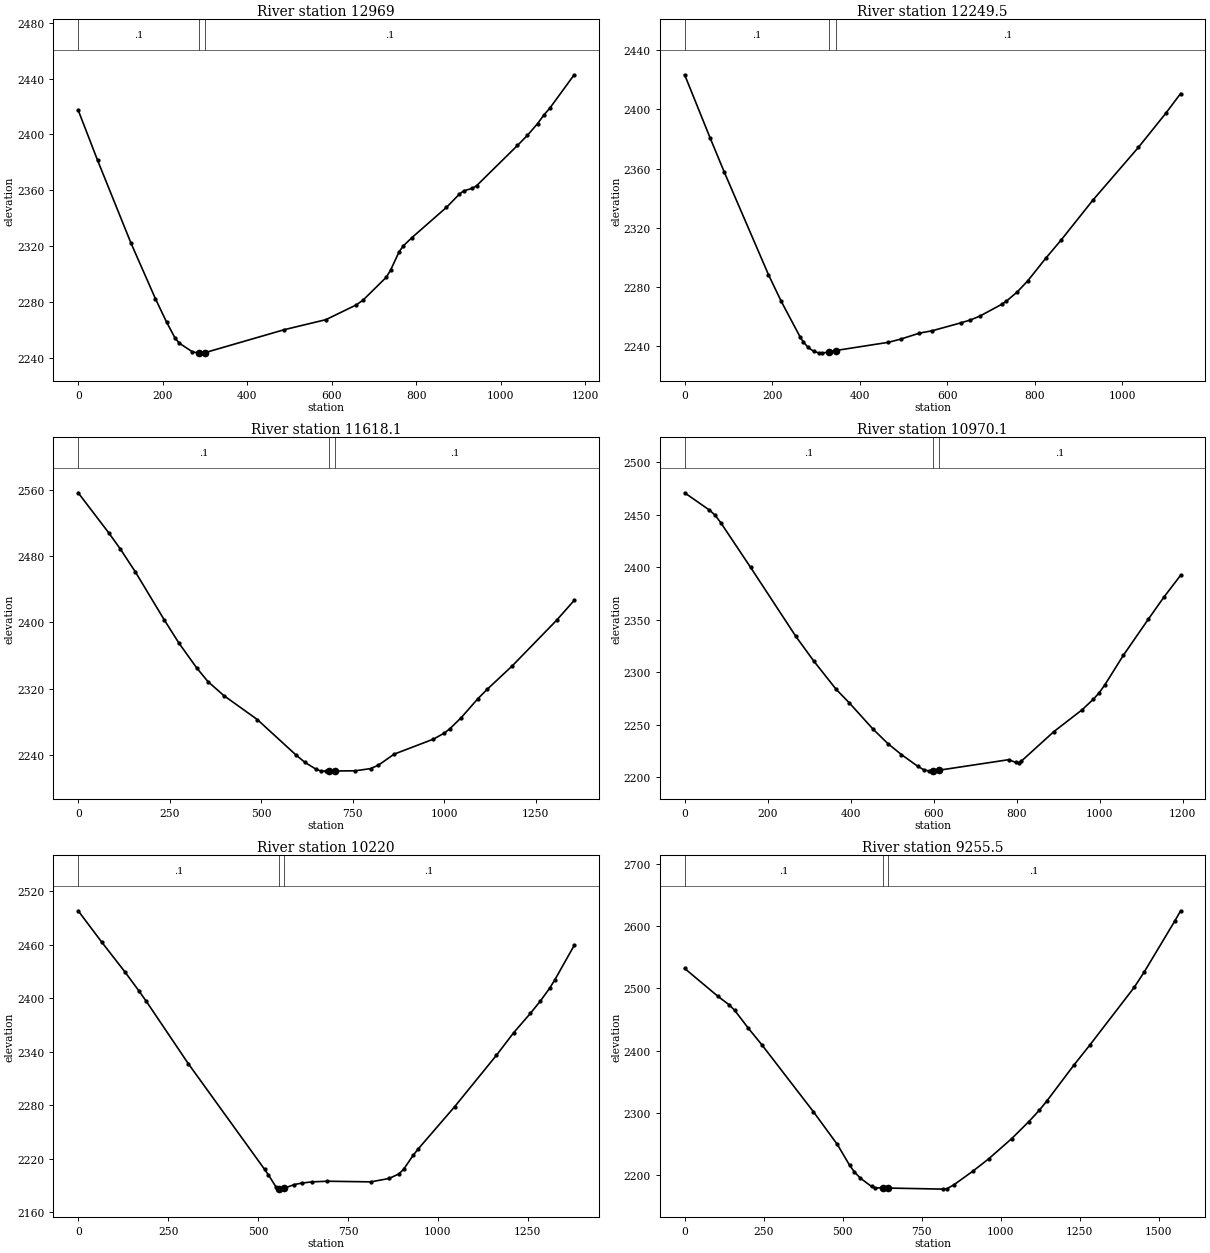
Type RM Length L Ch R = 1 ,12969,701.5,719.5,737.2
XS GIS Cut Line= 2
     2199602.908      380424.666     2199767.468      381587.093
#Sta/Elev= 30
       0 2417.35    45.8 2381.56   125.0 2322.24   182.7 2282.61   209.0 2265.92
   229.4 2254.34   239.5 2250.71   270.1 2244.62     285 2243.64     300 2243.98
   488.2 2260.44   586.3 2267.57   657.7 2278.04   674.1 2281.49   729.1 2297.85
   739.3 2302.87   759.7 2316.17   769.9 2320.43   790.0 2326.26   871.8 2347.90
   902.4 2357.38   912.6 2359.69   932.9 2361.51   943.2 2363.40  1039.8 2392.14
  1063.5 2399.43  1087.3 2407.73  1102.9 2414.12  1116.6 2418.91  1174.0 2442.66
#Mann= 3 , 0 , 0
       0     0.1       0     285   0.045       0     300     0.1       0
Bank Sta=     285,     300
Exp/Cntr=0.3,0.1

Type RM Length L Ch R = 1 ,12249.5,627,631.4,635.8
XS GIS Cut Line= 2
     2199203.761      380267.108     2198510.506      381163.437
#Sta/Elev= 30
       0 2423.28    57.8 2380.90    90.5 2357.56   191.4 2288.34   220.2 2270.50
   263.4 2246.44   270.6 2243.05   282.0 2239.19   294.8 2236.51   307.6 2235.34
   313.8 2235.31   329.8 2236.13   344.8 2237.06   465.0 2242.59   493.8 2244.80
   536.5 2248.82   565.8 2250.44   630.5 2255.72   652.2 2257.64   673.7 2260.21
   724.1 2268.24   734.6 2270.31   760.1 2276.71   784.1 2284.22   824.9 2299.37
   859.7 2311.56   933.0 2338.76  1036.6 2374.27  1099.0 2397.23  1133.1 2410.66
#Mann= 3 , 0 , 0
       0     0.1       0   329.8   0.045       0   344.8     0.1       0
Bank Sta=   329.8,   344.8
Exp/Cntr=0.3,0.1

Type RM Length L Ch R = 1 ,11618.1,650.8,648.1,645.4
XS GIS Cut Line= 2
     2199042.702      379671.889     2198020.326      380561.216
#Sta/Elev= 30
       0 2556.02    83.0 2508.08   114.5 2488.74   156.0 2460.89   234.9 2403.16
   275.1 2375.08   323.7 2345.18   354.5 2328.66   397.9 2311.82   489.2 2283.01
   596.3 2239.76   619.8 2231.27   649.8 2223.15   663.2 2220.89   676.6 2220.84
   686.3 2220.94   701.3 2221.01   756.9 2221.23   798.7 2223.88   820.2 2228.01
   863.1 2241.27   970.5 2259.37  1000.6 2266.75  1016.0 2272.13  1046.8 2285.40
  1091.5 2307.86  1118.2 2319.71  1185.2 2347.29  1306.9 2402.47  1355.0 2426.46
#Mann= 3 , 0 , 0
       0     0.1       0   686.3   0.045       0   701.3     0.1       0
Bank Sta=   686.3,   701.3
Exp/Cntr=0.3,0.1

Type RM Length L Ch R = 1 ,10970.1,762.4,750,737.6
XS GIS Cut Line= 2
     2198522.925      379173.542     2197722.716      380060.532
#Sta/Elev= 30
       0 2470.82    59.7 2454.38    73.3 2449.55    86.9 2442.40   158.7 2399.90
   267.9 2334.08   310.8 2310.79   364.9 2283.76   396.6 2270.87   453.4 2246.02
   489.5 2232.10   522.1 2221.65   561.0 2210.65   575.3 2207.34   589.1 2205.91
   597.9 2206.02   612.9 2206.80   780.5 2216.80   797.0 2214.28   804.1 2214.00
   811.3 2215.54   889.3 2243.53   957.3 2264.30   984.5 2274.38   998.1 2280.35
  1011.7 2287.80  1056.4 2316.00  1116.7 2350.48  1154.4 2371.58  1194.6 2392.34
#Mann= 3 , 0 , 0
       0     0.1       0   597.9   0.045       0   612.9     0.1       0
Bank Sta=   597.9,   612.9
Exp/Cntr=0.3,0.1

Type RM Length L Ch R = 1 ,10220,960.7,964.6,968.4
XS GIS Cut Line= 3
     2197726.217      378537.472     2197565.158      379360.274
     2197204.526      379762.922
#Sta/Elev= 30
       0 2497.93    65.7 2462.72   130.6 2429.04   168.6 2408.26   189.2 2396.52
   306.0 2326.59   518.4 2207.87   528.7 2201.92   549.3 2188.62   557.6 2186.16
   559.6 2185.80   572.6 2186.73   600.7 2190.91   621.3 2192.56   650.2 2193.95
   692.8 2194.65   813.7 2193.95   864.2 2197.74   891.3 2202.77   904.8 2208.06
   931.9 2224.05   945.5 2230.93  1046.7 2278.26  1162.4 2335.69  1211.2 2361.42
  1257.3 2382.93  1284.4 2396.42  1311.1 2411.29  1325.6 2420.77  1379.0 2459.07
#Mann= 3 , 0 , 0
       0     0.1       0   557.6   0.045       0   572.6     0.1       0
Bank Sta=   557.6,   572.6
Exp/Cntr=0.3,0.1

Type RM Length L Ch R = 1 ,9255.5,1055.8,1045.1,1034.3
XS GIS Cut Line= 3
     2197094.711      378060.436     2196670.284      379158.025
     2196539.281      379528.336
#Sta/Elev= 30
       0 2532.13   104.2 2487.81   141.0 2473.61   158.6 2464.64   201.6 2436.02
   245.0 2409.05   407.4 2301.99   483.1 2249.46   521.8 2216.11   537.3 2205.10
   556.4 2195.12   591.4 2181.88   602.2 2179.66   628.4 2179.48   643.4 2179.38
   818.8 2177.64   829.6 2178.22   851.2 2184.28   913.8 2207.14   962.4 2226.42
  1035.3 2258.95  1089.4 2286.23  1121.9 2304.04  1147.2 2319.90  1231.8 2376.88
  1281.6 2408.64  1422.4 2501.56  1454.5 2526.54  1550.9 2608.13  1569.6 2624.72
#Mann= 3 , 0 , 0
       0     0.1       0   628.4   0.045       0   643.4     0.1       0
Bank Sta=   628.4,   643.4
Exp/Cntr=0.3,0.1

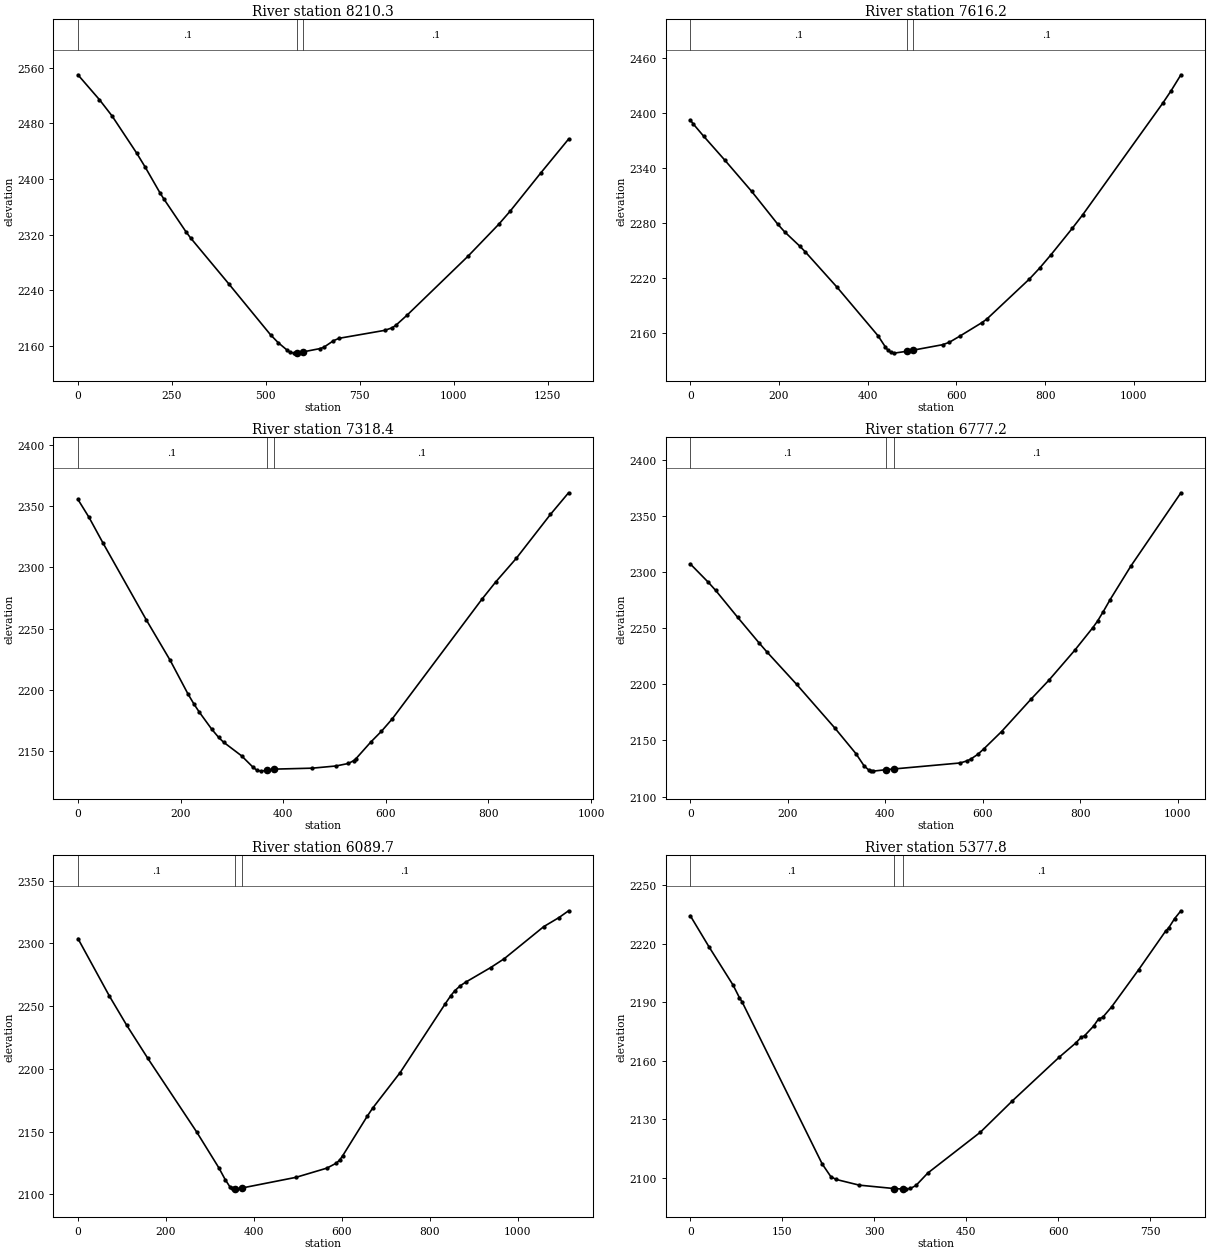
Type RM Length L Ch R = 1 ,8210.3,605.6,594.1,582.6
XS GIS Cut Line= 2
     2195853.029      377949.255     2195947.563      379251.734
#Sta/Elev= 30
       0 2549.53    57.1 2513.94    90.7 2490.57   156.2 2437.24   179.0 2417.03
   219.0 2379.45   229.2 2370.86   287.2 2324.43   300.0 2315.19   401.3 2249.52
   512.6 2176.27   532.9 2164.99   556.6 2154.28   563.3 2151.60   575.5 2149.88
   583.8 2150.01   598.8 2151.61   644.3 2156.40   654.4 2158.29   680.2 2167.71
   694.9 2171.15   816.4 2182.56   836.6 2186.30   846.8 2190.10   876.7 2204.70
  1038.0 2288.87  1120.1 2334.88  1150.5 2353.72  1231.5 2408.28  1305.9 2457.16
#Mann= 3 , 0 , 0
       0     0.1       0   583.8   0.045       0   598.8     0.1       0
Bank Sta=   583.8,   598.8
Exp/Cntr=0.3,0.1

Type RM Length L Ch R = 1 ,7616.2,295.9,297.9,299.8
XS GIS Cut Line= 2
     2195124.761      378414.927     2195726.982      379342.768
#Sta/Elev= 30
       0 2392.35     6.2 2388.30    30.3 2374.56    78.5 2348.15   138.5 2314.35
   196.9 2278.81   212.4 2270.40   247.0 2254.57   259.1 2248.52   331.3 2209.60
   423.2 2156.89   439.6 2144.82   445.1 2141.34   451.7 2138.88   459.7 2137.89
   487.5 2139.86   502.5 2141.14   569.2 2147.11   584.1 2149.73   608.2 2156.57
   656.8 2170.97   668.4 2174.98   764.7 2218.81   787.4 2230.56   812.8 2244.99
   861.0 2273.93   885.0 2289.01  1065.6 2410.91  1084.1 2424.27  1106.2 2441.66
#Mann= 3 , 0 , 0
       0     0.1       0   487.5   0.045       0   502.5     0.1       0
Bank Sta=   487.5,   502.5
Exp/Cntr=0.3,0.1

Type RM Length L Ch R = 1 ,7318.4,546.9,541.1,535.3
XS GIS Cut Line= 2
     2194984.709      378656.515     2195446.879      379493.323
#Sta/Elev= 30
       0 2355.55    21.7 2340.84    48.5 2320.20   133.1 2257.24   179.9 2223.99
   214.5 2196.58   226.0 2188.45   236.4 2181.85   260.6 2167.92   274.3 2161.08
   283.7 2157.26   318.9 2146.07   340.9 2136.89   348.6 2134.33   356.1 2133.59
   367.5 2134.18   382.5 2135.22   456.7 2136.01   502.9 2137.80   527.0 2139.85
   537.5 2142.19   541.8 2143.76   570.6 2157.31   591.5 2166.18   612.4 2176.23
   787.1 2273.97   814.3 2288.24   854.0 2307.36   920.8 2343.36   956.0 2360.97
#Mann= 3 , 0 , 0
       0     0.1       0   367.5   0.045       0   382.5     0.1       0
Bank Sta=   367.5,   382.5
Exp/Cntr=0.3,0.1

Type RM Length L Ch R = 1 ,6777.2,692.1,687.5,682.9
XS GIS Cut Line= 2
     2194508.534      379066.166     2195187.784      379808.439
#Sta/Elev= 30
       0 2307.11    37.1 2290.70    52.0 2283.57    96.9 2259.71   141.8 2236.43
   156.7 2229.00   218.0 2199.96   296.6 2160.97   339.5 2138.39   356.2 2127.55
   366.1 2123.63   369.9 2122.95   375.2 2122.71   401.8 2124.01   416.8 2124.61
   553.9 2129.99   568.2 2131.95   575.5 2133.52   589.7 2137.66   602.6 2142.75
   638.3 2157.89   698.4 2186.57   735.0 2203.38   788.2 2230.12   825.5 2250.36
   835.3 2256.28   847.0 2264.68   861.2 2275.45   903.7 2305.28  1006.2 2370.40
#Mann= 3 , 0 , 0
       0     0.1       0   401.8   0.045       0   416.8     0.1       0
Bank Sta=   401.8,   416.8
Exp/Cntr=0.3,0.1

Type RM Length L Ch R = 1 ,6089.7,707.4,711.9,716.3
XS GIS Cut Line= 2
     2194091.881      379706.902     2194995.213      380361.642
#Sta/Elev= 30
       0 2303.88    71.6 2258.02   110.7 2234.92   158.9 2208.44   269.8 2149.92
   320.4 2121.26   334.8 2111.93   346.0 2105.89   349.3 2104.92   357.4 2104.32
   358.4 2104.26   372.4 2105.12   495.6 2113.63   566.2 2121.00   587.9 2125.01
   595.4 2127.55   602.4 2131.03   657.7 2162.21   670.2 2168.76   732.8 2197.13
   835.7 2252.11   848.2 2258.50   857.3 2262.40   869.7 2266.31   882.2 2269.22
   938.5 2280.74   969.5 2287.82  1059.4 2313.40  1093.8 2320.56  1115.7 2325.97
#Mann= 3 , 0 , 0
       0     0.1       0   357.4   0.045       0   372.4     0.1       0
Bank Sta=   357.4,   372.4
Exp/Cntr=0.3,0.1

Type RM Length L Ch R = 1 ,5377.8,704,717.7,731.4
XS GIS Cut Line= 2
     2193829.285      380253.102     2194378.987      380834.316
#Sta/Elev= 30
       0 2234.22    30.2 2218.44    69.8 2198.67    80.2 2192.19    84.4 2190.13
   215.1 2107.07   229.0 2100.65   237.3 2099.19   275.5 2096.23   331.6 2094.51
   346.6 2094.22   351.6 2094.19   358.8 2094.52   368.0 2096.06   387.3 2102.44
   473.0 2123.35   525.3 2139.43   601.6 2161.78   628.2 2168.93   637.3 2171.92
   642.9 2172.76   657.6 2177.67   665.9 2181.46   672.3 2182.11   687.0 2187.53
   731.0 2206.53   775.1 2226.37   780.2 2228.04   789.8 2232.77   800.0 2236.74
#Mann= 3 , 0 , 0
       0     0.1       0   331.6   0.045       0   346.6     0.1       0
Bank Sta=   331.6,   346.6
Exp/Cntr=0.3,0.1

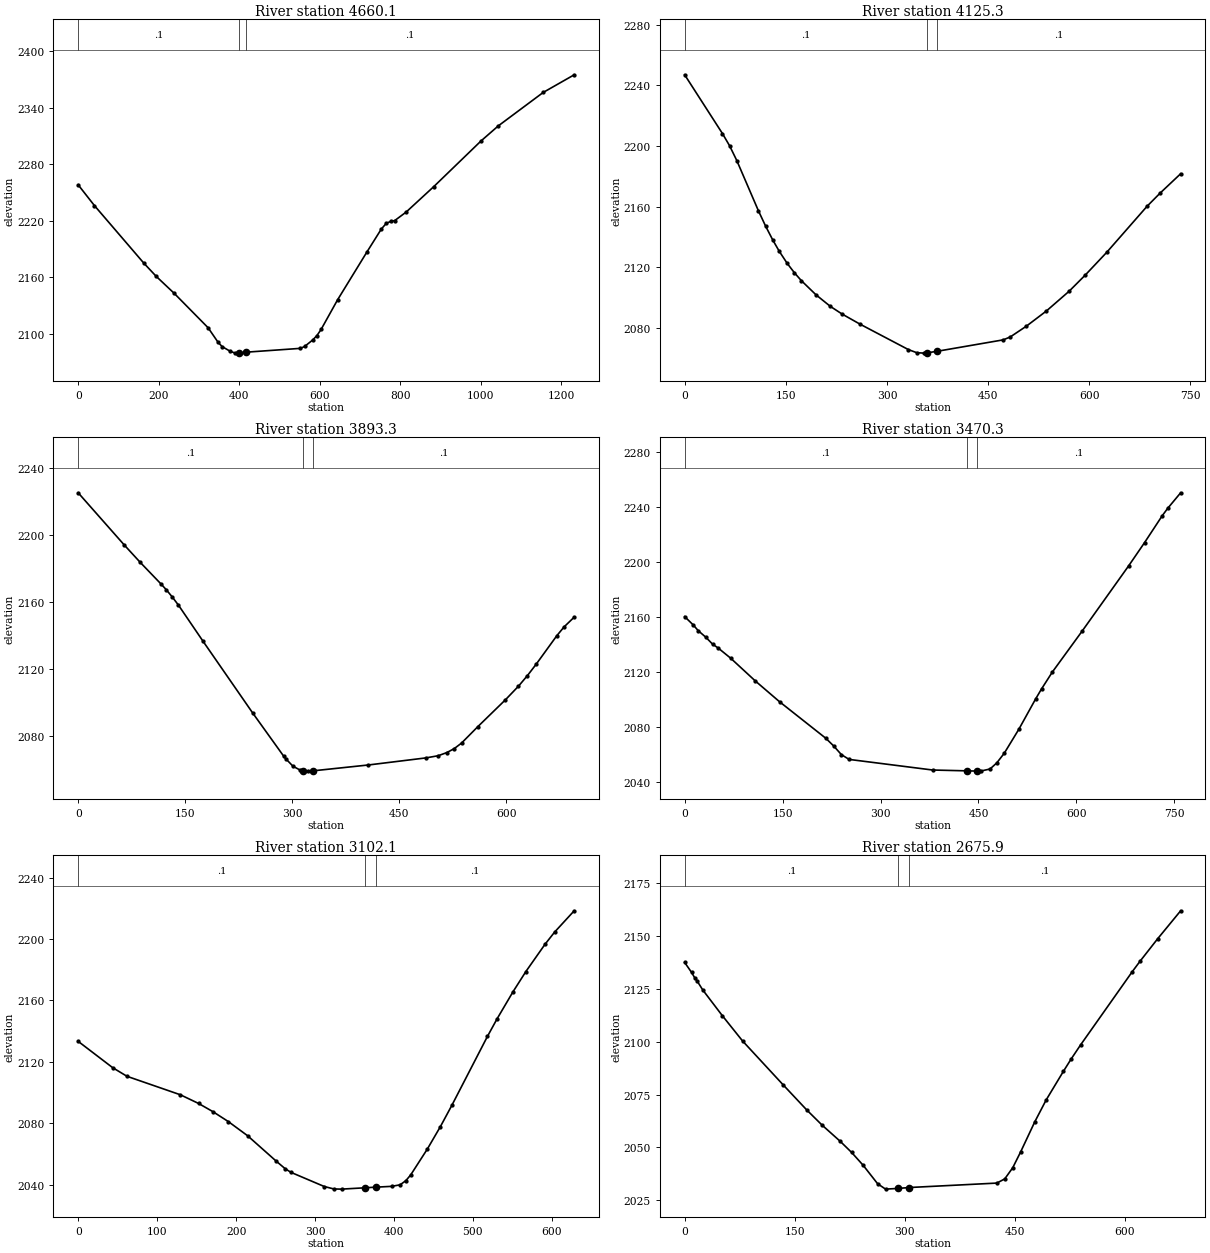
Type RM Length L Ch R = 1 ,4660.1,538.5,534.8,531
XS GIS Cut Line= 3
     2193332.102      380137.560     2193464.840      380912.770
     2193755.758      381250.969
#Sta/Elev= 30
       0 2258.17    40.2 2236.22   163.1 2174.99   193.8 2160.99   238.4 2143.00
   322.8 2106.37   347.5 2090.99   357.7 2086.32   378.2 2081.25   388.5 2079.68
   398.7 2079.39   400.8 2079.47   415.8 2080.35   552.4 2084.46   562.6 2086.44
   583.1 2093.47   593.4 2098.11   603.6 2104.51   644.6 2136.03   717.0 2186.48
   753.3 2211.21   765.6 2217.27   777.6 2219.54   786.4 2220.16   815.0 2229.26
   883.6 2256.28  1001.2 2304.87  1044.2 2320.90  1155.6 2356.37  1232.6 2375.11
#Mann= 3 , 0 , 0
       0     0.1       0   400.8   0.045       0   415.8     0.1       0
Bank Sta=   400.8,   415.8
Exp/Cntr=0.3,0.1

Type RM Length L Ch R = 1 ,4125.3,228.5,232,235.5
XS GIS Cut Line= 2
     2192781.425      380376.679     2193020.487      381072.404
#Sta/Elev= 30
       0 2247.03    56.0 2208.25    66.6 2200.17    77.3 2190.40   109.3 2157.29
   120.0 2147.10   130.7 2137.87   140.4 2130.36   152.0 2122.50   162.7 2116.28
   172.9 2111.12   194.8 2101.68   216.1 2094.03   233.6 2088.95   260.3 2082.25
   331.8 2065.50   344.2 2063.45   354.9 2063.16   359.2 2063.33   374.2 2064.36
   472.4 2071.92   482.8 2073.82   506.7 2080.93   536.4 2090.96   570.2 2104.04
   594.1 2114.70   625.9 2129.71   685.9 2160.22   705.3 2168.93   735.6 2181.65
#Mann= 3 , 0 , 0
       0     0.1       0   359.2   0.045       0   374.2     0.1       0
Bank Sta=   359.2,   374.2
Exp/Cntr=0.3,0.1

Type RM Length L Ch R = 1 ,3893.3,406.1,423,439.9
XS GIS Cut Line= 2
     2192625.918      380487.171     2192752.779      381170.585
#Sta/Elev= 30
       0 2225.02    64.7 2193.78    87.0 2183.43   116.0 2170.57   123.2 2167.23
   131.8 2162.79   140.5 2157.90   175.1 2136.23   244.4 2093.55   287.7 2067.82
   290.6 2066.26   300.9 2061.71   311.2 2059.33   314.3 2059.02   321.4 2058.77
   329.3 2058.96   406.5 2062.44   487.0 2066.66   504.3 2067.96   516.6 2069.87
   526.8 2072.20   537.1 2075.52   559.7 2085.24   598.7 2101.42   616.9 2109.52
   629.5 2115.88   641.5 2122.53   670.6 2139.66   680.9 2144.98   694.9 2150.72
#Mann= 3 , 0 , 0
       0     0.1       0   314.3   0.045       0   329.3     0.1       0
Bank Sta=   314.3,   329.3
Exp/Cntr=0.3,0.1

Type RM Length L Ch R = 1 ,3470.3,357.8,368.2,378.6
XS GIS Cut Line= 2
     2192551.315      380599.730     2192148.667      381243.967
#Sta/Elev= 30
       0 2160.44    13.2 2154.32    20.8 2150.19    32.2 2145.51    42.8 2140.39
    51.3 2137.59    70.3 2130.25   108.4 2113.55   145.4 2098.49   216.1 2071.98
   228.0 2066.47   240.0 2060.08   251.9 2056.57   379.9 2048.85   432.7 2048.25
   447.7 2048.09   453.2 2048.05   467.8 2049.61   478.1 2054.04   489.5 2061.04
   511.8 2078.43   537.6 2100.56   546.6 2107.80   563.1 2120.05   609.1 2150.06
   680.0 2197.30   704.4 2214.22   731.6 2233.86   740.1 2239.30   759.7 2250.47
#Mann= 3 , 0 , 0
       0     0.1       0   432.7   0.045       0   447.7     0.1       0
Bank Sta=   432.7,   447.7
Exp/Cntr=0.3,0.1

Type RM Length L Ch R = 1 ,3102.1,440.1,426.2,412.2
XS GIS Cut Line= 2
     2192449.777      380445.673     2191928.086      380795.802
#Sta/Elev= 30
       0 2133.27    43.6 2116.16    61.8 2110.52   129.4 2098.49   152.4 2092.85
   170.5 2087.54   190.2 2081.02   214.5 2071.84   251.0 2055.18   262.3 2050.28
   269.6 2047.93   311.8 2038.71   323.9 2037.13   333.6 2037.02   362.7 2037.87
   377.7 2038.32   396.9 2038.82   407.8 2039.82   415.1 2042.55   421.2 2046.26
   442.3 2063.13   458.8 2077.70   473.3 2091.55   518.5 2136.57   530.7 2148.01
   551.0 2165.73   567.1 2178.74   591.5 2196.61   603.6 2204.50   628.3 2218.32
#Mann= 3 , 0 , 0
       0     0.1       0   362.7   0.045       0   377.7     0.1       0
Bank Sta=   362.7,   377.7
Exp/Cntr=0.3,0.1

Type RM Length L Ch R = 1 ,2675.9,696.7,681.5,666.2
XS GIS Cut Line= 2
     2191998.111      380043.025     2191753.021      380673.257
#Sta/Elev= 30
       0 2137.50     9.3 2132.84    13.9 2130.12    17.1 2128.66    24.7 2124.48
    51.5 2112.26    78.9 2100.38   134.1 2079.67   166.2 2067.82   187.3 2060.58
   212.1 2052.89   227.7 2047.61   243.3 2041.58   263.1 2032.82   273.9 2030.28
   291.3 2030.62   306.3 2031.04   425.6 2033.14   436.4 2035.12   447.3 2040.40
   458.1 2047.91   477.3 2062.08   492.9 2072.49   516.3 2085.96   526.7 2091.71
   539.7 2098.45   610.3 2133.16   620.6 2137.96   644.9 2148.72   676.2 2161.93
#Mann= 3 , 0 , 0
       0     0.1       0   291.3   0.045       0   306.3     0.1       0
Bank Sta=   291.3,   306.3
Exp/Cntr=0.3,0.1