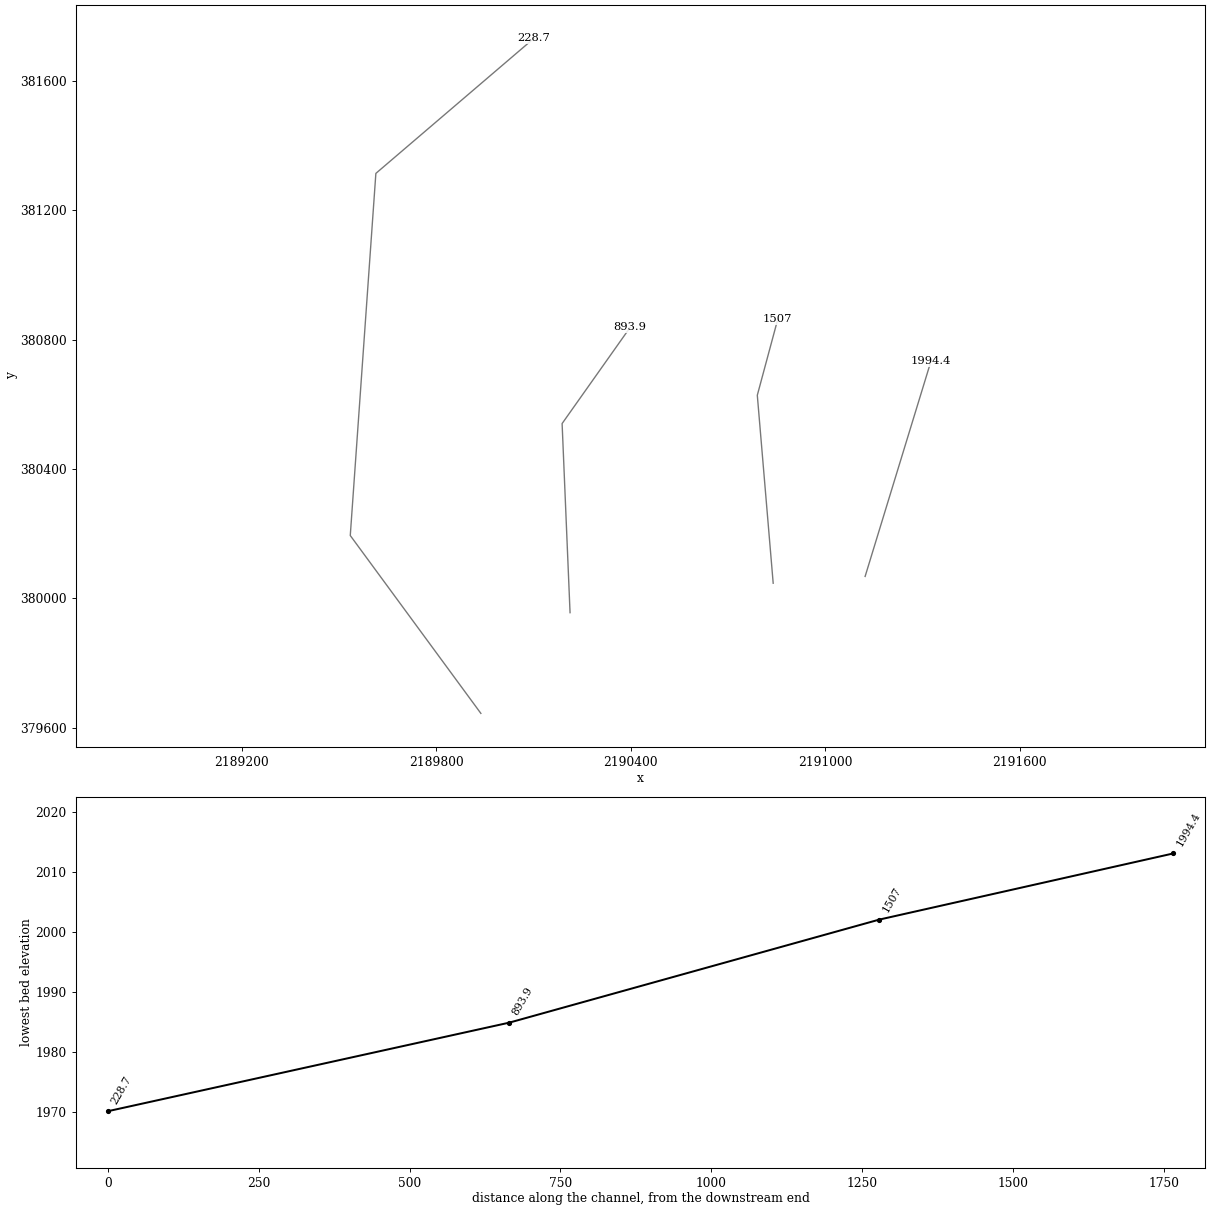
HEC-RAS study SpiceRun.prj: SpiceRun

--- SpiceRun.g01 (geometry) --- (continued)

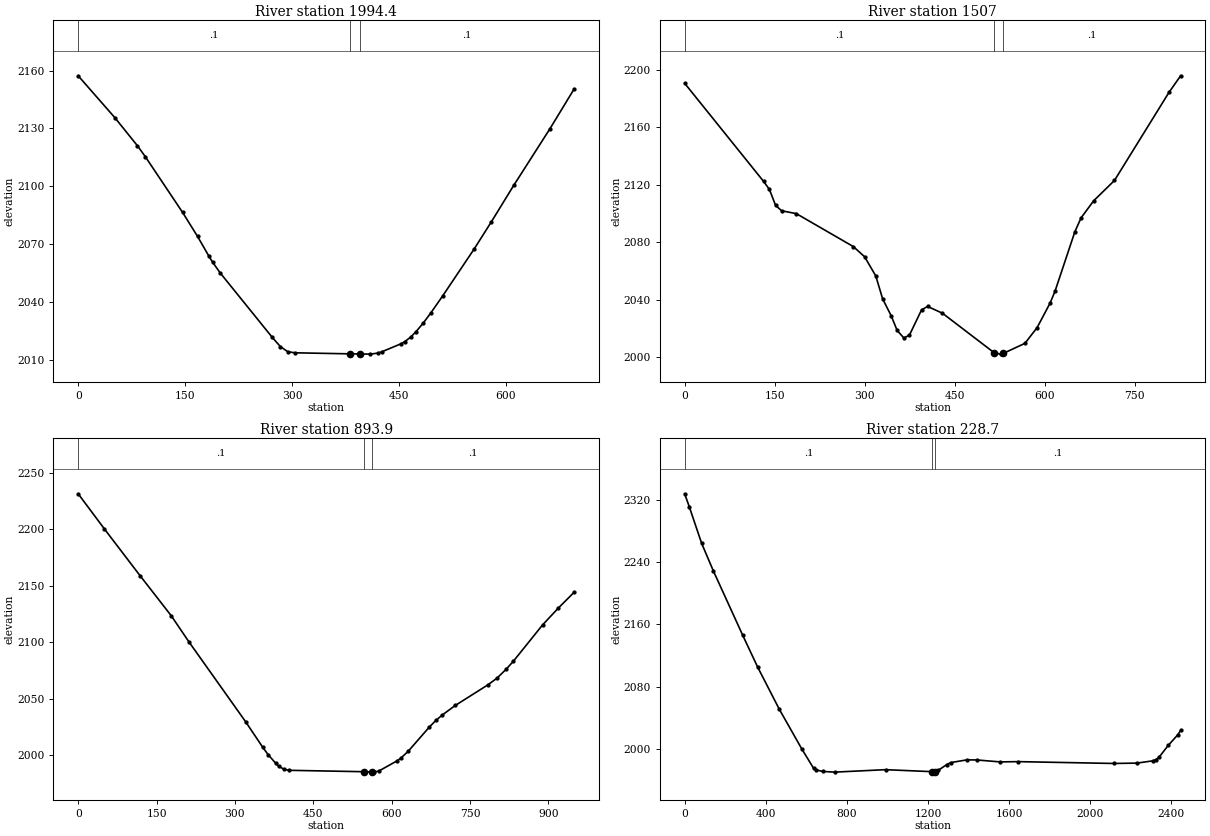
Type RM Length L Ch R = 1 ,1994.4,479.1,487.5,495.8
XS GIS Cut Line= 2
     2191122.789      380067.534     2191325.864      380732.779
#Sta/Elev= 30
       0 2157.28    51.3 2135.64    83.0 2121.08    94.1 2115.41   146.3 2086.57
   167.4 2074.07   183.5 2063.71   188.5 2060.75   199.1 2055.18   272.1 2021.80
   283.5 2017.02   294.1 2014.30   304.7 2013.77   380.8 2013.24   395.8 2013.19
   409.9 2013.09   420.8 2013.66   425.8 2014.30   452.5 2018.41   458.1 2019.59
   466.2 2021.89   473.6 2024.64   484.1 2029.26   494.7 2034.51   511.2 2043.25
   555.2 2067.48   579.2 2081.48   610.8 2100.48   661.8 2129.96   695.6 2150.48
#Mann= 3 , 0 , 0
       0     0.1       0   380.8   0.045       0   395.8     0.1       0
Bank Sta=   380.8,   395.8
Exp/Cntr=0.3,0.1

Type RM Length L Ch R = 1 ,1507,613.7,613.1,612.2
XS GIS Cut Line= 3
     2190839.185      380046.526     2190790.167      380627.740
     2190853.190      380862.326
#Sta/Elev= 30
       0 2190.49   131.5 2122.22   141.2 2116.62   151.4 2105.60   161.5 2101.80
   186.0 2099.82   281.0 2076.88   299.7 2069.84   318.4 2056.43   329.8 2040.50
   343.9 2028.86   354.0 2018.51   365.1 2013.32   374.3 2015.18   394.6 2032.83
   404.7 2035.24   429.4 2030.53     516 2002.90   526.3 2002.06     531 2002.61
   566.8 2009.56   587.2 2020.55   608.8 2037.61   617.0 2045.87   650.0 2087.18
   660.4 2096.90   681.3 2108.73   716.0 2122.90   806.8 2184.17   826.2 2195.70
#Mann= 3 , 0 , 0
       0     0.1       0     516   0.045       0     531     0.1       0
Bank Sta=     516,     531
Exp/Cntr=0.3,0.1

Type RM Length L Ch R = 1 ,893.9,667.8,665.2,662.5
XS GIS Cut Line= 3
     2190212.455      379955.493     2190187.946      380540.208
     2190398.023      380837.817
#Sta/Elev= 30
       0 2231.55    50.0 2200.52   118.6 2158.89   178.1 2123.51   211.8 2100.46
   320.3 2029.70   353.2 2006.97   363.4 2000.50   378.5 1992.55   383.6 1990.28
   393.7 1987.44   403.8 1986.50   547.8 1985.25   562.8 1984.94   565.5 1984.89
   575.6 1985.88   610.5 1994.90   617.2 1997.10   631.6 2003.27   672.3 2024.88
   684.7 2030.67   697.0 2035.51   721.8 2043.95   783.6 2062.02   801.6 2068.09
   819.2 2076.03   833.0 2083.10   889.2 2115.45   919.5 2130.45   949.5 2144.32
#Mann= 3 , 0 , 0
       0     0.1       0   547.8   0.045       0   562.8     0.1       0
Bank Sta=   547.8,   562.8
Exp/Cntr=0.3,0.1

Type RM Length L Ch R = 1 ,228.7,225.5,228.7,231.8
XS GIS Cut Line= 4
     2189937.275      379644.157     2189534.379      380194.032
     2189613.357      381313.663     2190100.967      381731.231
#Sta/Elev= 30
       0 2328.04    22.3 2311.74    83.8 2264.25   141.6 2228.81   286.4 2146.06
   360.3 2105.01   466.7 2050.97   577.7 1999.94   635.7 1975.11   648.2 1972.88
   681.7 1971.01   739.3 1970.13   991.0 1973.29  1220.3 1970.72  1235.3 1970.83
  1250.7 1972.45  1292.4 1979.83  1312.6 1982.43  1392.2 1985.89  1440.2 1985.80
  1555.6 1983.28  1644.8 1983.62  2117.2 1981.27  2231.7 1981.74  2307.8 1984.62
  2323.4 1986.05  2339.4 1989.18  2385.4 2004.61  2432.0 2018.09  2446.1 2023.70
#Mann= 3 , 0 , 0
       0     0.1       0  1220.3   0.045       0  1235.3     0.1       0
Bank Sta=  1220.3,  1235.3
Exp/Cntr=0.3,0.1